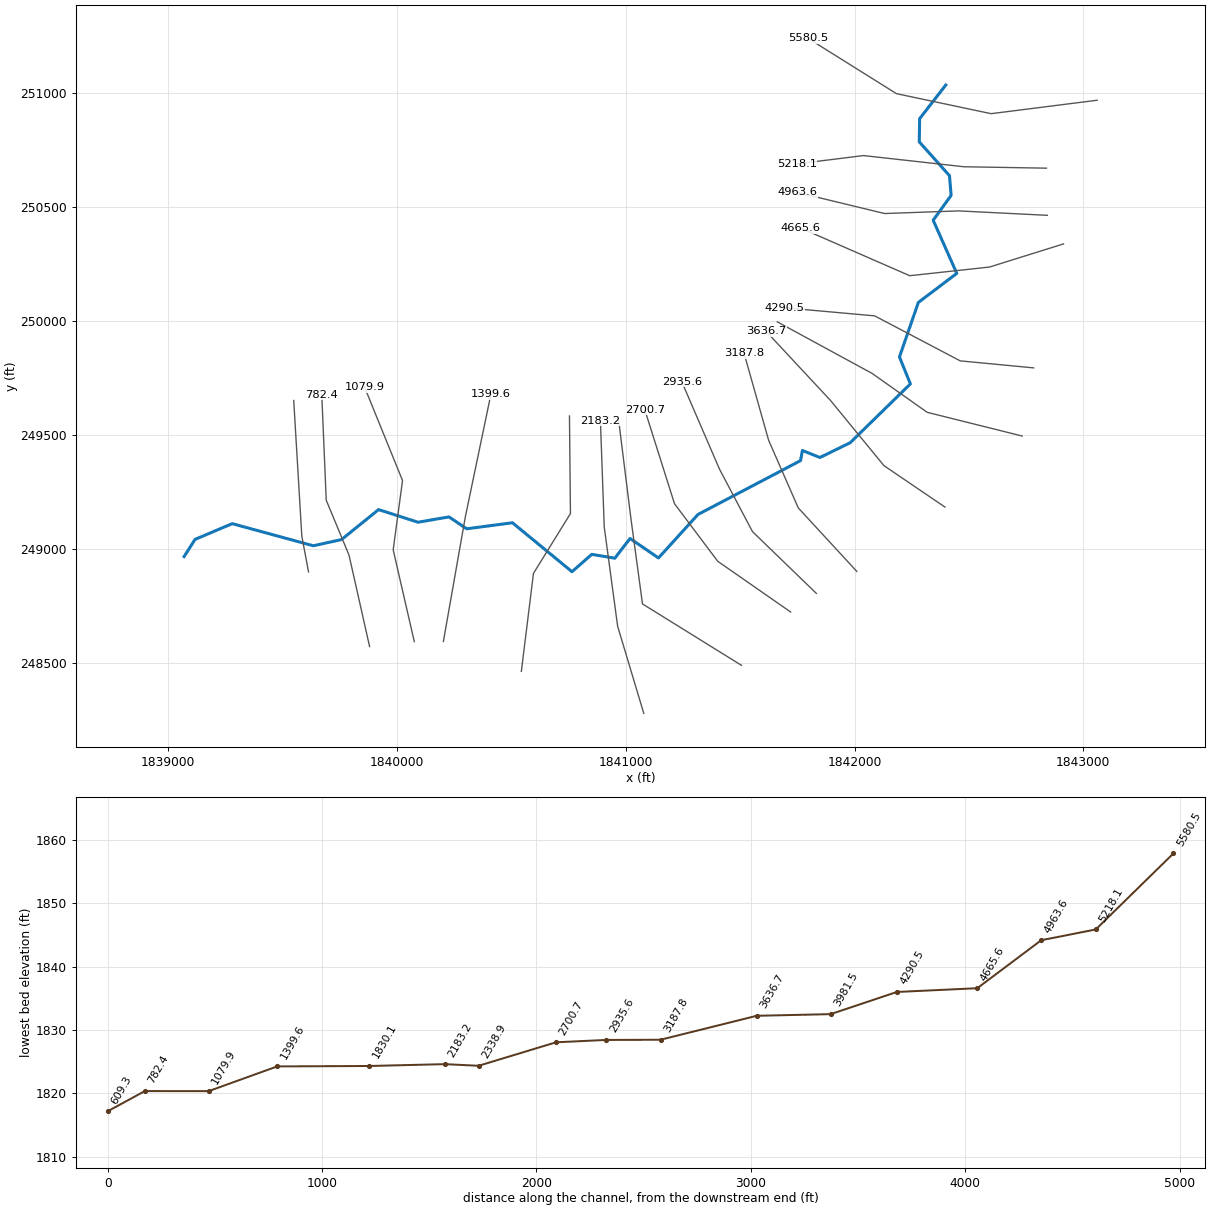
--- MilamFk1.prj (project) ---

Proj Title=MilamFk1
Current Plan=p01
Default Exp/Contr=0,0
English Units
Geom File=g01
Flow File=f01
Plan File=p01
BEGIN DESCRIPTION:
END DESCRIPTION:
DSS Export Rating Curves= 0
DSS Export Rating Curve Sorted= 0
DSS Export Volume Flow Curves= 0
DXF OffsetX= 0
DXF OffsetY= 0
DXF ScaleX= 0
DXF ScaleY= 0

--- MilamFk1.p01 (plan) ---

Plan Title=Floodplain
Program Version=4.00
Geom File=g01
Flow File=f01
K Sum by GR=0
Std Step Tol=0.01
Critical Tol=0.01
Num of Std Step Trials=20
Max Error Tol=0.3
Flow Tol Ratio=0.001
Split Flow NTrial=30
Split Flow Tol=0.02
Split Flow Ratio=0.02
Log Output Level=0
Friction Slope Method=1
Unsteady Friction Slope Method=2
Unsteady Bridges Friction Slope Method=1
Global Log Level=0
CheckData=False
Run HTab=0
Run UNet=0
Run PostProcess=0
UNET Theta=0
UNET Theta Warmup=0
UNET ZTol=0
UNET ZSATol=0
UNET MxIter=0
UNET MaxInSteps=0
UNET DtIC=0
UNET DtMin=0
UNET MaxCRTS=0
UNET WFStab=0
UNET SFStab=0
UNET WFX=0
UNET SFX=0
UNET DSS MLevel=0
UNET DZMax Abort=0
UNET Convert EG Bridges=0
UNET Use Existing IB Tables=0
UNET Froude Limit=0
UNET Froude Power=0
Write IC File=0
Echo Input=False
Echo Output=False
Write Detailed=0

--- MilamFk1.f01 (steady flow) ---

Flow Title=NFF Regression Equation
Program Version=4.00
Number of Profiles= 1
Profile Names=P100yr
River Rch & RM=MilamFk1,Main            ,5580.5
556.7477
River Rch & RM=MilamFk1,Main            ,4290.5
572.8424
River Rch & RM=MilamFk1,Main            ,4290.5
678.1466
River Rch & RM=MilamFk1,Main            ,2183.2
715.6827
River Rch & RM=MilamFk1,Main            ,1830.1
  821.31
Boundary for River Rch & Prof#=MilamFk1,Main            , 1
Up Type= 0
Dn Type= 1
Dn Known WS=1822.1
DSS Import GetInterval= 0
DSS Import GetPeak= 0
DSS Import FillOption= 0

--- MilamFk1.g01 (geometry) ---

Geom Title=USGS 10m DEM
Program Version=4.00

River Reach=MilamFk1        ,Main
Reach XY= 30
     1842398.717      251033.547     1842284.469      250886.282
     1842282.868      250784.654     1842414.905      250636.613
     1842422.106       250550.19     1842343.685       250441.36
     1842446.913      250208.496     1842278.867      250081.261
     1842196.244      249842.618     1842244.064      249724.434
     1841981.053      249466.888     1841848.523      249401.989
      1841772.01      249432.731     1841763.813      249388.326
     1841315.566      249152.521     1841142.833      248962.043
      1841018.52      249047.376     1840952.102      248960.952
      1840851.13      248977.755     1840764.851      248901.736
     1840504.605      249116.216     1840304.724      249089.788
     1840227.102      249141.802     1840091.865      249118.596
     1839919.319      249173.818     1839757.373      249042.575
     1839634.133      249015.422     1839279.568      249112.264
     1839117.197      249043.375     1839069.184      248968.154

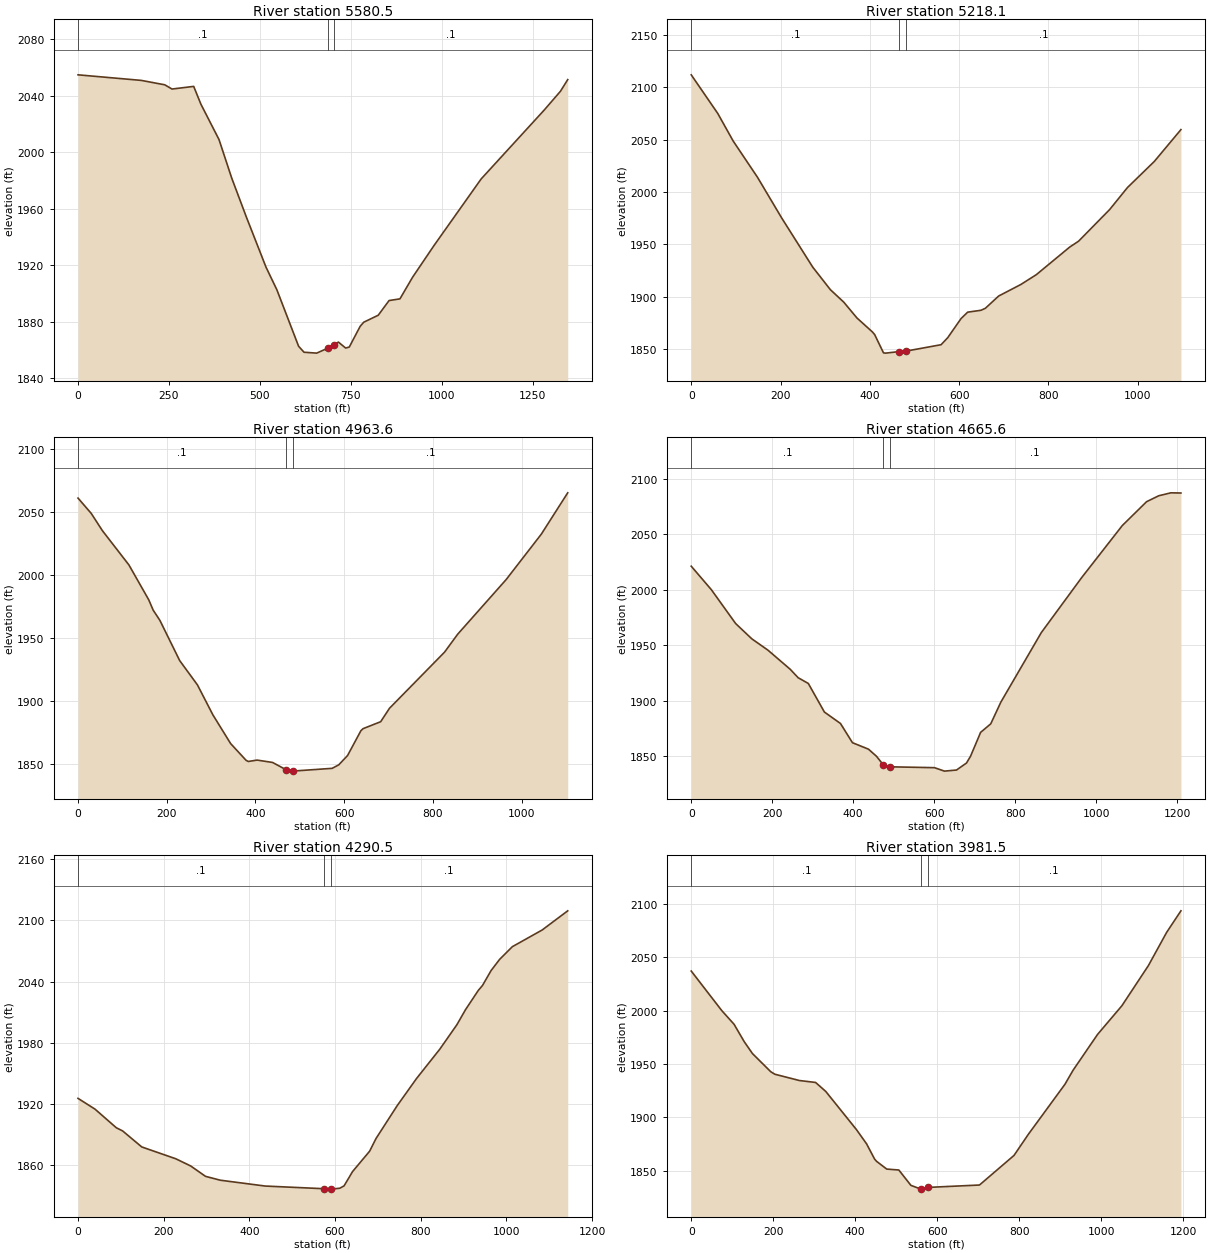
Type RM Length L Ch R = 1 ,5580.5  ,370.3,362.4,355.9
XS GIS Cut Line= 4
      1843060.29      250966.927      1842596.92      250908.133
     1842183.234      250995.777     1841796.638      251238.121
#Sta/Elev= 30
       0  2054.7   173.9 2050.76   238.5 2047.64   258.4 2044.65     318 2046.52
   337.9 2033.89   387.6 2008.92   422.4 1981.77   462.1 1954.58   516.8 1918.68
   546.7 1902.65   606.4 1862.73   621.3 1858.51   656.1 1857.88   687.9 1861.54
   702.9 1863.66   715.8 1865.68   735.7 1861.47   745.7 1862.18   775.5 1876.79
   785.5 1879.76   825.3 1884.68   855.1 1895.07     885 1896.25   919.7 1911.55
   979.2 1934.19  1108.2 1981.05  1281.8 2029.85  1326.4 2043.13  1346.2 2051.32
#Mann= 3 , 0 , 0
       0      .1       0   687.9    .045       0   702.9      .1       0
Bank Sta=687.9,702.9
XS Rating Curve= 0 ,0
Exp/Cntr=0.3,0.1

Type RM Length L Ch R = 1 ,5218.1  ,233,254.5,267.7
XS GIS Cut Line= 4
     1842838.987      250669.416     1842477.758       250675.61
     1842038.982      250724.582     1841747.147      250688.136
#Sta/Elev= 30
       0 2111.91    59.4 2075.01      94  2048.6   148.5 2013.93   202.9 1974.88
   272.2 1928.08   311.8 1906.47   341.5  1894.7   371.2 1879.49   405.9 1866.11
   410.9 1863.58   430.7  1846.1   435.7 1845.88   466.1 1847.37   481.1  1847.8
   559.7 1853.93   574.6 1860.67   604.4 1878.92   619.2 1885.04     649 1886.83
   658.9 1888.77   688.7 1900.48   738.3 1911.49     773 1920.88   847.6 1947.21
   867.6 1952.86   937.4  1983.2   977.2 2004.19  1037.1 2029.03  1096.9 2059.54
#Mann= 3 , 0 , 0
       0      .1       0   466.1    .045       0   481.1      .1       0
Bank Sta=466.1,481.1
XS Rating Curve= 0 ,0
Exp/Cntr=0.3,0.1

Type RM Length L Ch R = 1 ,4963.6  ,305.7,298.1,295.3
XS GIS Cut Line= 4
     1842842.803      250462.889     1842454.429      250482.238
     1842131.304      250470.698     1841750.477       250563.02
#Sta/Elev= 30
       0 2061.32    29.9  2049.1    54.8  2035.5   114.7  2008.2   159.5  1980.4
   169.5 1972.18   184.5 1964.12   229.3 1932.04   269.2 1912.78   304.1 1888.91
     344 1866.12   378.9 1852.77   383.9 1851.86   403.8 1852.95   438.6 1851.08
   469.8 1845.16   483.4 1844.18   484.8 1844.22   572.9  1846.4   587.8 1849.18
   607.7 1856.59   637.6 1876.24   642.6 1877.95   682.3 1883.48   702.2 1894.17
   826.3  1938.8     856  1953.1   965.2 1996.53  1044.5 2032.66    1104 2065.52
#Mann= 3 , 0 , 0
       0      .1       0   469.8    .045       0   484.8      .1       0
Bank Sta=469.8,484.8
XS Rating Curve= 0 ,0
Exp/Cntr=0.3,0.1

Type RM Length L Ch R = 1 ,4665.6  ,388.6,375.1,361.4
XS GIS Cut Line= 4
     1842913.281      250337.602     1842589.874        250236.3
     1842241.155      250198.345     1841765.031      250406.843
#Sta/Elev= 30
       0 2021.34    49.8  2000.1   109.6 1969.68   149.5 1955.89   189.4 1945.67
   244.2  1928.5   264.1 1920.78   289.1 1915.66   328.9 1889.85   368.6 1879.55
   398.2 1862.22   437.7 1856.41   457.5    1850   474.8 1842.07   489.8 1840.51
   600.8 1839.72   625.4 1836.61   655.1 1837.59   679.8 1843.92   689.7 1849.94
   714.7 1871.55   739.7 1879.23   764.6 1898.76   864.6 1961.49   964.6 2011.21
  1064.5 2057.92  1124.5 2079.45  1154.5  2084.8  1184.5 2087.46  1209.4  2087.3
#Mann= 3 , 0 , 0
       0      .1       0   474.8    .045       0   489.8      .1       0
Bank Sta=474.8,489.8
XS Rating Curve= 0 ,0
Exp/Cntr=0.3,0.1

Type RM Length L Ch R = 1 ,4290.5  ,312.6,309,305.4
XS GIS Cut Line= 4
     1842782.928      249794.614     1842461.927      249825.336
     1842087.626      250022.502     1841691.444      250058.122
#Sta/Elev= 30
       0 1925.18    39.7 1914.59    89.3 1896.35   104.2 1893.18   148.8 1877.46
   228.2 1865.85   262.9 1858.81   297.7 1848.57   332.4 1844.77   436.9 1839.05
     575 1836.41     590 1836.03   591.2 1836.02   611.1  1836.9   621.1  1839.2
     641 1853.28   680.8 1873.28   695.8  1885.8   745.5 1918.23   790.3 1944.67
     845 1973.71   884.8  1997.7   904.6 2012.28   934.5 2031.22   944.4 2036.14
   964.3  2050.7   984.2 2061.68    1014  2074.2  1083.6  2090.6  1143.3 2109.44
#Mann= 3 , 0 , 0
       0      .1       0     575    .045       0     590      .1       0
Bank Sta=575,590
XS Rating Curve= 0 ,0
Exp/Cntr=0.3,0.1

Type RM Length L Ch R = 1 ,3981.5  ,297.8,344.7,289
XS GIS Cut Line= 4
     1842732.579      249496.162     1842317.437      249599.947
     1842076.506      249770.452     1841662.109       249996.35
#Sta/Elev= 30
       0 2037.22    74.6 2000.06   104.5 1987.27   129.4 1970.88   149.3 1959.81
   194.1  1942.7     204 1940.37   263.7 1934.48   303.5 1932.64   328.4 1924.17
     403 1888.48   427.9 1875.03   447.6 1860.63   452.5 1858.54   477.1 1851.34
   506.6 1850.46   536.1 1836.04   560.7 1832.52   561.7 1832.53   576.7 1834.12
   703.4 1836.37   787.7 1864.17   822.4 1883.83   911.9 1930.89   931.7 1944.05
   991.4 1977.65    1051 2004.68  1115.6 2042.33  1160.3 2073.62    1195 2093.74
#Mann= 3 , 0 , 0
       0      .1       0   561.7    .045       0   576.7      .1       0
Bank Sta=561.7,576.7
XS Rating Curve= 0 ,0
Exp/Cntr=0.3,0.1

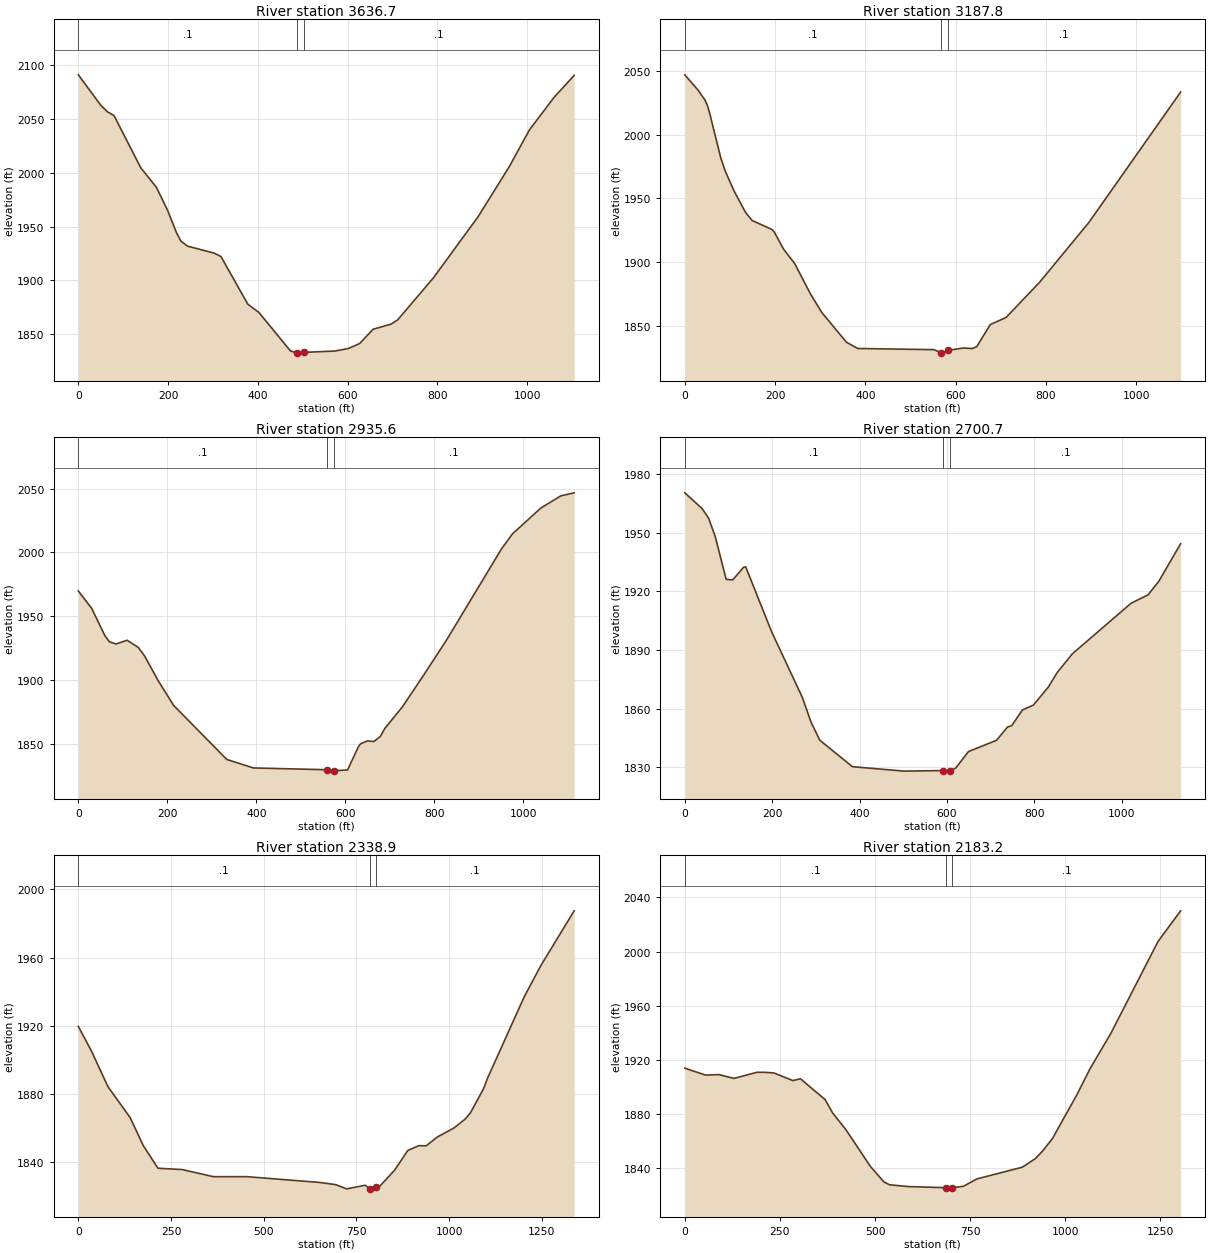
Type RM Length L Ch R = 1 ,3636.7  ,482.6,448.9,439.4
XS GIS Cut Line= 4
     1842395.276      249184.805     1842128.399       249366.43
     1841894.882       249651.84      1841613.66      249954.273
#Sta/Elev= 30
       0 2091.26    49.7 2063.12    64.6 2056.92    79.5 2053.37   139.1 2004.75
   173.8 1986.67   198.7 1965.33   218.5 1944.52   228.5 1936.49   243.4  1931.8
     303  1925.3   317.8 1922.12   377.6 1877.81   402.6 1869.99   472.3 1834.42
   487.3 1832.26   487.8 1832.28   502.8 1832.96     572 1834.23   601.9 1836.61
   626.8 1841.22   656.7 1854.47   696.6 1859.23   711.5 1863.23   791.1 1902.36
   890.6 1959.18   960.3 2005.97    1005 2040.02  1059.8 2070.26  1104.6 2090.77
#Mann= 3 , 0 , 0
       0      .1       0   487.8    .045       0   502.8      .1       0
Bank Sta=487.8,502.8
XS Rating Curve= 0 ,0
Exp/Cntr=0.3,0.1

Type RM Length L Ch R = 1 ,3187.8  ,245,252.3,261.9
XS GIS Cut Line= 4
     1842009.787      248903.102      1841754.03      249181.099
     1841624.298      249477.628     1841516.806      249859.411
#Sta/Elev= 30
       0 2046.98    29.8  2034.8    44.7 2027.15    49.7 2023.27    54.7 2017.37
    79.5 1981.98    89.5 1971.43   109.4  1955.6   134.2 1939.14   149.1 1932.62
   193.8 1925.44   198.8 1923.17   218.7 1910.15   243.6 1898.64   278.3 1874.93
   303.2 1860.49   357.9 1837.08   382.7 1832.14     552  1831.2   567.1 1828.77
     572 1828.48   582.1  1830.6   616.8  1832.5   636.7 1832.07   646.6 1833.62
   676.5 1850.89   711.3 1856.43   785.7 1884.11   894.8 1931.06    1098 2033.42
#Mann= 3 , 0 , 0
       0      .1       0   567.1    .045       0   582.1      .1       0
Bank Sta=567.1,582.1
XS Rating Curve= 0 ,0
Exp/Cntr=0.3,0.1

Type RM Length L Ch R = 1 ,2935.6  ,231.2,234.8,238.5
XS GIS Cut Line= 4
     1841832.876      248806.925     1841553.872      249077.313
     1841409.314      249351.603     1841244.965      249733.511
#Sta/Elev= 30
       0 1969.68    29.9  1956.1    59.8  1934.6    69.7 1929.87    84.7 1928.12
   109.6 1931.07   134.5 1925.56   149.4 1918.48   179.3 1899.46   214.2 1879.99
   333.7 1837.58   393.4 1830.95   559.1 1829.53   565.7 1828.45   574.1 1828.78
   605.1 1829.35   629.7 1847.71   634.6 1849.95   649.4 1852.11   664.1 1851.66
   678.9 1855.67   688.7 1861.86   728.3 1878.78   777.8 1904.59   827.3 1931.07
     951 2002.61   975.8 2014.48  1040.1 2034.87  1084.6 2044.27  1114.4 2046.64
#Mann= 3 , 0 , 0
       0      .1       0   559.1    .045       0   574.1      .1       0
Bank Sta=559.1,574.1
XS Rating Curve= 0 ,0
Exp/Cntr=0.3,0.1

Type RM Length L Ch R = 1 ,2700.7  ,372.2,361.8,349.8
XS GIS Cut Line= 4
     1841720.671      248725.184     1841401.815      248947.506
     1841212.863      249199.632     1841083.131      249611.067
#Sta/Elev= 30
       0 1970.46    39.9 1962.34    54.8 1957.36    69.8 1947.99    94.7 1926.23
   109.6 1925.89   134.6 1932.39   139.5 1932.56   199.3 1899.12   269.1 1865.81
     289 1853.17     309 1843.92   383.7 1830.36   501.9 1828.08   592.2 1828.37
   607.2  1828.3   620.1  1829.6   649.6  1838.1   713.7 1843.84   738.5 1850.56
   748.4 1851.34   773.2 1859.41     798 1861.82   832.7 1871.21   852.5  1878.5
   887.2 1888.06  1021.1 1913.86  1060.8 1918.29  1085.6 1925.32  1135.2 1944.42
#Mann= 3 , 0 , 0
       0      .1       0   592.2    .045       0   607.2      .1       0
Bank Sta=592.2,607.2
XS Rating Curve= 0 ,0
Exp/Cntr=0.3,0.1

Type RM Length L Ch R = 1 ,2338.9  ,154.6,155.8,177.8
XS GIS Cut Line= 4
     1841505.686      248491.666     1841073.011       248760.66
     1841022.841      249131.365     1840966.683       249581.96
#Sta/Elev= 30
       0 1919.72      35  1905.5    79.9 1884.44   139.9 1866.26   174.8 1850.04
   214.8 1836.61   279.7 1835.85   364.6 1831.66   454.5 1831.67   649.1 1828.33
     694 1827.02     724 1824.52   773.8 1826.64   787.1 1824.39   788.8 1824.37
   802.1 1825.57   813.7 1826.16   853.6 1835.58   888.6 1846.97   918.5 1849.85
   938.4 1849.75   968.4  1854.9  1013.3 1860.21  1043.2 1865.36  1058.2 1869.21
  1093.1 1883.21  1103.1 1888.97  1202.9  1937.1  1247.8  1955.4  1337.6 1987.48
#Mann= 3 , 0 , 0
       0      .1       0   787.1    .045       0   802.1      .1       0
Bank Sta=787.1,802.1
XS Rating Curve= 0 ,0
Exp/Cntr=0.3,0.1

Type RM Length L Ch R = 1 ,2183.2  ,366.1,353.1,314.3
XS GIS Cut Line= 4
     1841078.586      248281.252     1840964.308      248663.106
     1840905.776      249097.918     1840889.052       249563.39
#Sta/Elev= 30
       0 1913.91    54.8  1908.8    89.7 1909.17   129.5 1906.34   189.3 1910.86
   209.3 1910.86   234.2 1910.36     284 1904.75   303.9 1906.08   368.7 1890.77
   388.6 1880.83   423.5  1868.5   488.3 1841.21   523.2 1829.98   538.2 1827.84
     588 1826.51     687 1825.69   692.7 1824.63     702  1825.6   732.6 1826.77
   767.5 1832.15   886.9  1840.8   921.6 1847.19   941.4 1853.09   966.2 1861.95
  1030.6 1894.34  1065.2 1913.58  1119.8 1939.64  1243.6 2007.35  1303.1 2030.04
#Mann= 3 , 0 , 0
       0      .1       0     687    .045       0     702      .1       0
Bank Sta=687,702
XS Rating Curve= 0 ,0
Exp/Cntr=0.3,0.1

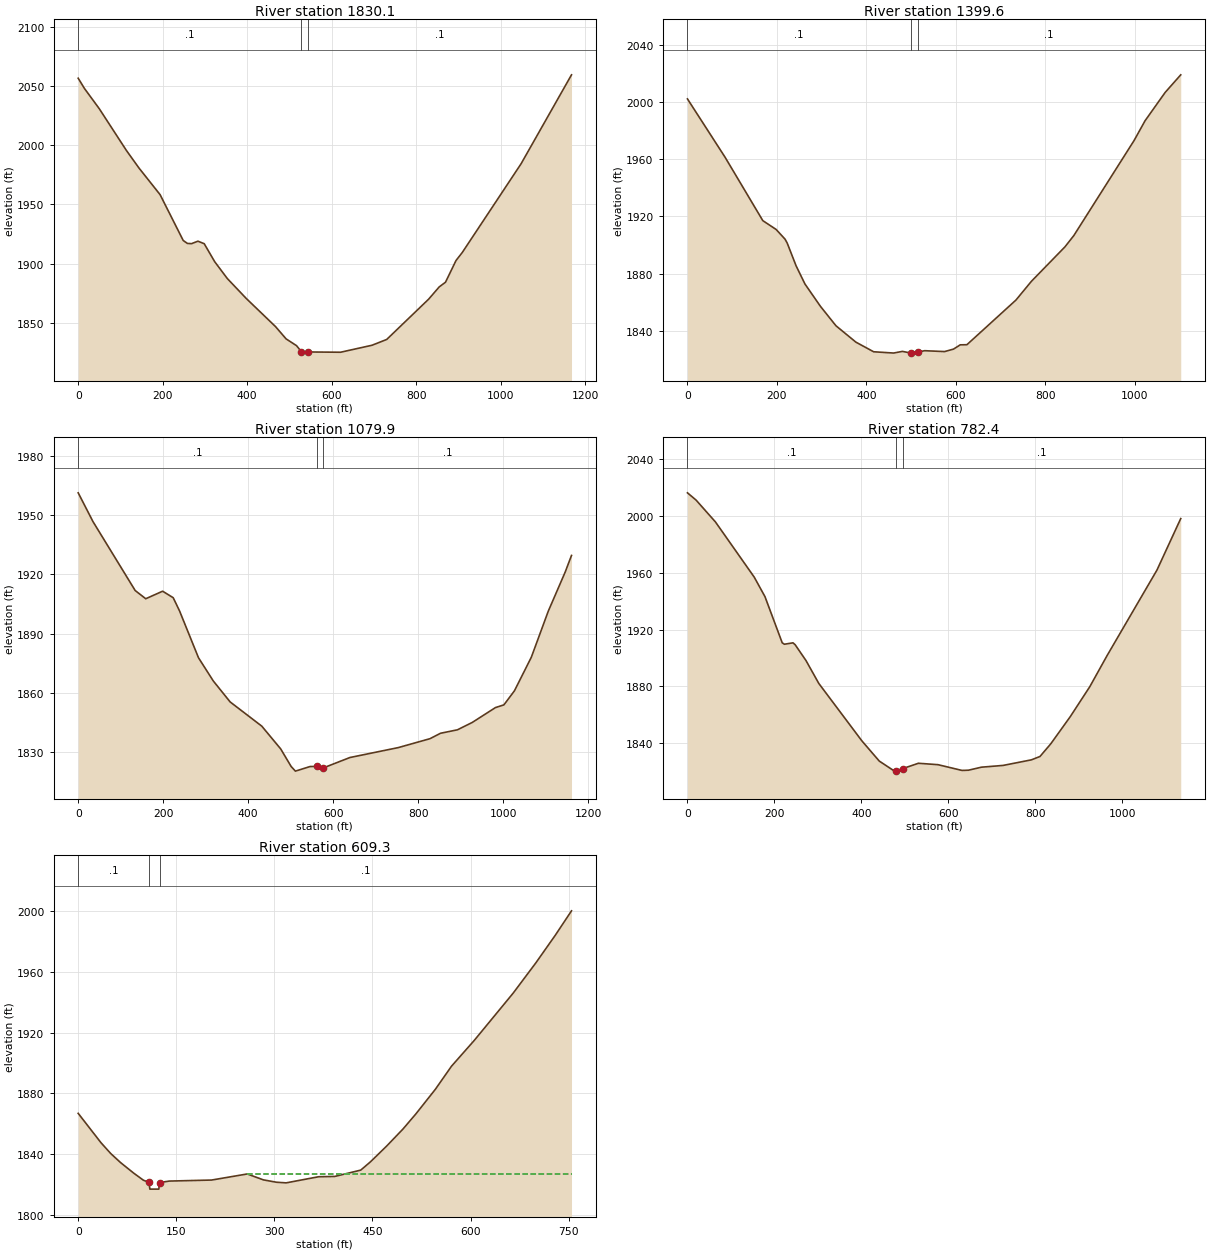
Type RM Length L Ch R = 1 ,1830.1  ,421.4,430.5,438.8
XS GIS Cut Line= 4
     1840543.432      248465.211      1840596.39      248894.448
     1840758.051      249156.451      1840753.79      249583.981
#Sta/Elev= 30
       0 2056.65    14.9 2047.94    49.7 2030.99   114.3 1995.52   144.2 1980.63
   193.9 1958.26   248.6 1919.54   258.5 1917.05   268.4 1916.87   283.4 1918.93
   298.3 1916.83   323.1 1901.64     353 1887.39   397.7 1870.59   467.2 1846.75
   492.1 1836.41   516.9 1830.65   528.6 1825.47   531.8 1824.34   543.6 1825.32
   621.2 1825.09   695.7 1831.01   730.4 1835.89   829.8 1869.98   854.7  1880.3
   869.6 1884.27   894.5 1902.61   909.4 1909.44  1048.6 1984.41  1167.9 2059.53
#Mann= 3 , 0 , 0
       0      .1       0   528.6    .045       0   543.6      .1       0
Bank Sta=528.6,543.6
XS Rating Curve= 0 ,0
Exp/Cntr=0.3,0.1

Type RM Length L Ch R = 1 ,1399.6  ,318.1,319.8,321.5
XS GIS Cut Line= 3
     1840202.598      248595.952     1840298.716      249142.765
     1840410.415      249679.189
#Sta/Elev= 30
       0 2002.39    84.3 1961.44   168.5 1917.11   198.3 1910.91   218.1 1904.18
   223.1 1901.37   242.9 1885.48   262.7 1872.74   297.4 1857.05   332.1 1843.44
   376.7 1831.96   416.4 1825.22     461 1824.33   480.8 1825.49   499.9  1824.3
   500.7 1824.27   514.9 1825.01   530.4 1825.97   575.1 1825.36     595  1827.1
     610 1830.08   624.9 1830.16   734.5 1861.43   769.4 1874.67   844.1 1898.71
     864 1906.64   998.5 1973.11  1023.4 1987.13  1068.3 2006.95  1103.1 2019.26
#Mann= 3 , 0 , 0
       0      .1       0   499.9    .045       0   514.9      .1       0
Bank Sta=499.9,514.9
XS Rating Curve= 0 ,0
Exp/Cntr=0.3,0.1

Type RM Length L Ch R = 1 ,1079.9  ,285.6,297.4,309.2
XS GIS Cut Line= 4
     1840075.423      248595.679     1839983.194      248997.577
     1840024.053       249301.14     1839857.767      249711.115
#Sta/Elev= 30
       0 1961.23    34.8 1946.66   134.1 1911.78     159 1907.62   198.7 1911.44
   223.6 1908.14   238.5 1901.48   283.2 1877.73     318    1866   357.7 1855.38
   432.1 1843.14   476.6 1831.62   501.3 1822.69   511.2 1820.37   545.7 1822.69
   562.3 1822.78   577.3 1822.03   639.6 1827.26   753.4 1832.28     828 1836.79
   852.9 1839.54   892.6 1841.28   927.4    1845   982.1 1852.53    1002 1853.91
  1026.8 1861.02  1066.6 1878.04  1106.4 1901.31  1146.2  1921.1  1161.1 1929.53
#Mann= 3 , 0 , 0
       0      .1       0   562.3    .045       0   577.3      .1       0
Bank Sta=562.3,577.3
XS Rating Curve= 0 ,0
Exp/Cntr=0.3,0.1

Type RM Length L Ch R = 1 ,782.4   ,177.6,173.1,168.6
XS GIS Cut Line= 4
     1839880.065      248573.914     1839790.001      248974.832
     1839690.532      249214.983     1839671.021      249677.668
#Sta/Elev= 30
       0 2016.32    19.8 2011.22    64.4  1995.8   153.5 1956.97   178.2 1943.22
   217.8 1910.75   222.8 1909.72   242.6 1910.71   247.5 1909.41   272.3 1898.32
     302 1882.08     401 1841.67   440.9 1827.46   475.9 1820.38   480.2 1820.72
   495.2 1822.19   530.9 1825.91   575.9 1824.92   630.9 1820.88   645.8 1821.02
   675.8 1823.16   725.6  1824.4   790.4 1828.31   810.3 1830.68   835.2 1839.63
     880 1858.76   924.8 1879.81   964.6 1901.74  1079.2 1961.92  1133.9 1998.21
#Mann= 3 , 0 , 0
       0      .1       0   480.2    .045       0   495.2      .1       0
Bank Sta=480.2,495.2
XS Rating Curve= 0 ,0
Exp/Cntr=0.3,0.1

Type RM Length L Ch R = 1 ,609.3   ,600.8,609.3,617.8
XS GIS Cut Line= 3
     1839613.179       248900.99     1839583.823      249057.607
     1839548.417      249651.615
#Sta/Elev= 30
       0 1866.96    34.9 1847.65    49.8 1840.55    64.7 1834.67    84.6  1827.8
    99.6 1823.08   108.3 1821.63   109.6  1817.2   123.3  1817.2   124.5 1821.52
   139.4 1822.49     204 1823.16   258.5 1827.16   283.3 1823.27   303.2 1821.73
     318 1821.31   367.6 1825.33   392.4 1825.54   432.1 1829.69     447 1835.15
   471.8 1845.52   496.6 1856.63   516.4 1866.59   546.1  1882.7   570.9 1897.93
   605.6 1914.82   665.2 1945.91   699.9  1965.8   729.6 1983.92   754.4 1999.96
#Mann= 3 , 0 , 0
       0      .1       0   108.3    .045       0   124.5      .1       0
#XS Ineff= 2 , 0
                          257.93         1827.18
Permanent Ineff=
       F       F
Bank Sta=108.3,124.5
XS Rating Curve= 0 ,0
Exp/Cntr=0.3,0.1

Chan Stop Cuts=-1
Use User Specified Reach Order=0